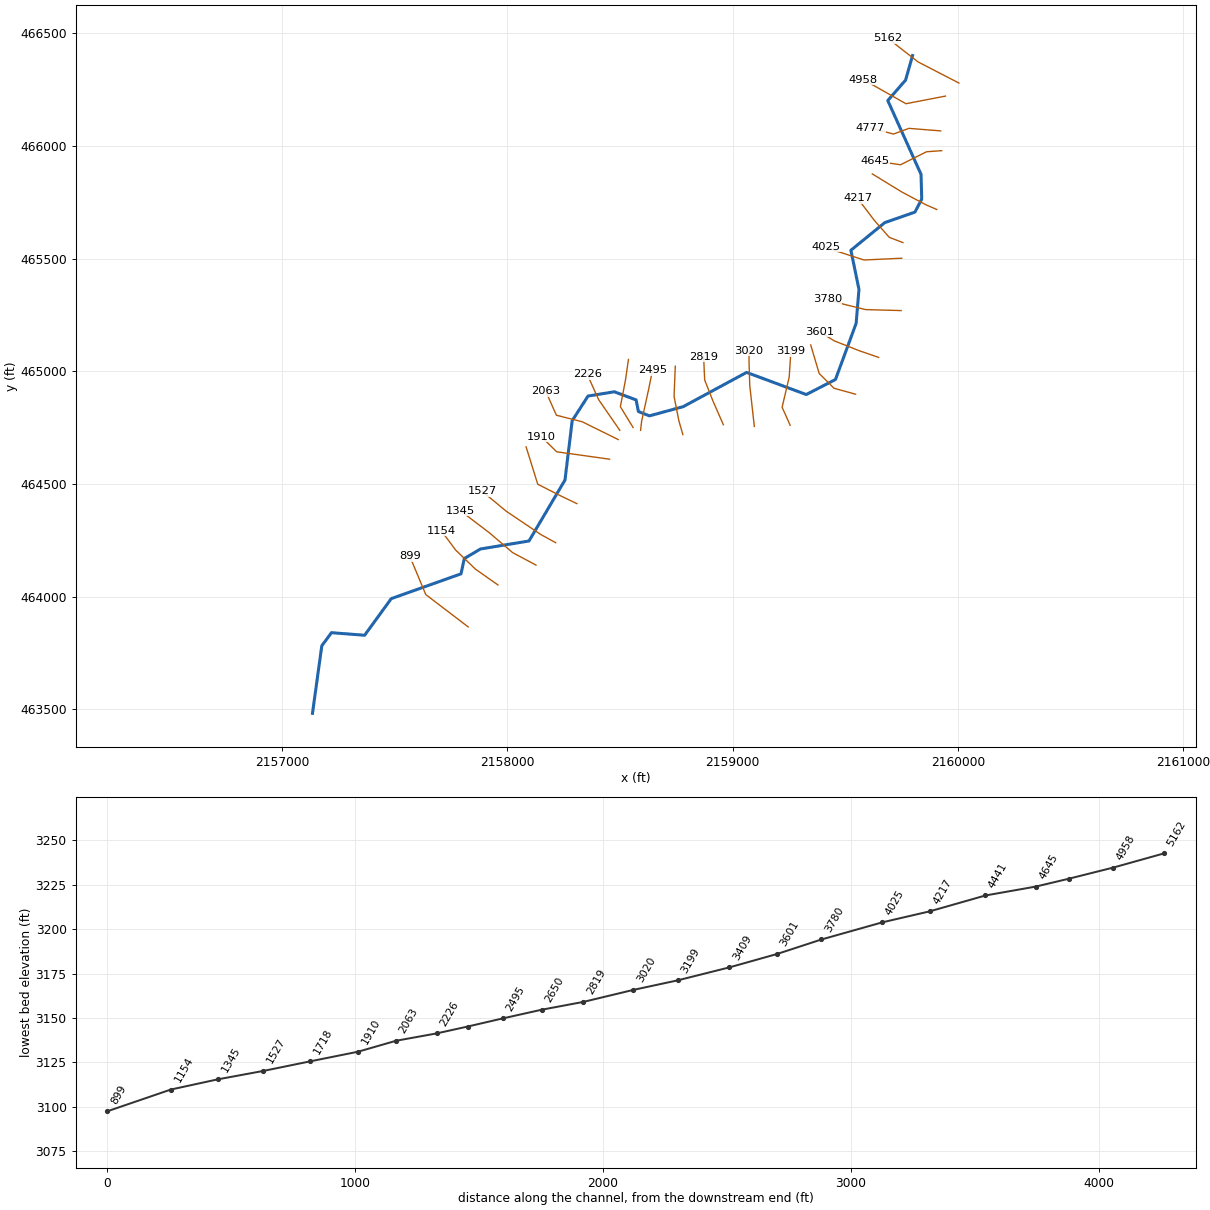
--- TMBLNGRCKRN.prj (project) ---

Proj Title=TMBLNGRCKRN
Current Plan=p01
Default Exp/Contr=0,0
English Units
Geom File=g01
Flow File=f01
Plan File=p01
Background Map Layer=Inundation Boundary (01pct Value_0)
Background Map Layer=Inundation Boundary (01pct Value_0)
BEGIN DESCRIPTION:
----------MODEL BY WOOD PLC 2021----------
Stream Name: Tumbling Rock Run
Flood Zone: Approximate
Pocahontas County, WV
HEC-RAS Version: RAS 6.0
Vertical Datum: NAVD88
Projection: NAD 1983 StatePlane West Virginia S FIPS 4702 (US Feet)
Terrain: 1-meter LIDAR (FEMA Region III 3DEP collected 2016-2018)
Land Use: 2019 NLCD
Hydrologic Method:
WV 2010 Regional Regression Equations
Model Notes:
Model snaps to CRANBRYRVSF at the downstream
END DESCRIPTION:
DSS File=dss
DSS Export Rating Curves= 0
DSS Export Rating Curve Sorted= 0
DSS Export Volume Flow Curves= 0
DXF OffsetX= 0
DXF OffsetY= 0
DXF ScaleX= 0
DXF ScaleY= 0

--- TMBLNGRCKRN.p01 (plan) ---

Plan Title=Floodplain
Program Version=6.00
Short Identifier=Floodplain
Geom File=g01
Flow File=f01
Subcritical Flow
K Sum by GR= 0
Std Step Tol= 0.01
Critical Tol= 0.01
Num of Std Step Trials= 20
Max Error Tol= 0.3
Flow Tol Ratio= 0.001
Split Flow NTrial= 30
Split Flow Tol= 0.02
Split Flow Ratio= 0.02
Log Output Level= 0
Friction Slope Method= 1
Unsteady Friction Slope Method= 2
Unsteady Bridges Friction Slope Method= 1
Parabolic Critical Depth
Global Vel Dist= 0 , 0 , 0
Global Log Level= 0
CheckData=True
Encroach Param=-1 ,0,0, 0
Computation Interval=1MIN
Output Interval=1HOUR
Instantaneous Interval=1HOUR
Mapping Interval=1HOUR
Computation Time Step Use Courant=        0
Computation Time Step Use Time Series=    0
Computation Time Step Count To Double=0
Computation Time Step Max Doubling=0
Computation Time Step Max Halving=0
Computation Time Step Residence Courant=0
Run HTab= 0
Run UNet= 0
Run Sediment= 0
Run PostProcess= 0
Run WQNet= 0
Run RASMapper=-1
UNET Theta= 1
UNET Theta Warmup= 1
UNET ZTol= 0.02
UNET ZSATol= 0.02
UNET MxIter= 20
UNET Max Iter WO Improvement= 0
UNET MaxInSteps= 0
UNET DtIC= 0
UNET DtMin= 0
UNET MaxCRTS= 20
UNET WFStab= 2
UNET SFStab= 1
UNET WFX= 1
UNET SFX= 1
UNET Gravity=32.174
UNET 1D Methodology=Finite Difference
UNET DSS MLevel= 4
UNET Pardiso=0
UNET DZMax Abort= 100
UNET Use Existing IB Tables=-1
UNET Froude Reduction=False
UNET Froude Limit= 0.8
UNET Froude Power= 4
UNET D1 Cores= 0
UNET WindReference=Eulerian
UNET WindDragFormulation=Hsu (1988)
UNET D2 Coriolis=0
UNET D2 Cores= 0
UNET D2 Theta= 1
UNET D2 Theta Warmup= 1
UNET D2 Z Tol= 0.01
UNET D2 Volume Tol= 0.01
UNET D2 Max Iterations= 20
UNET D2 Equation= 0
UNET D2 RampUpFraction=0.1
UNET D2 TimeSlices= 1
UNET D2 Turbulence Formulation=None
UNET D2 Eddy Viscosity=0.3
UNET D2 Transverse Eddy Viscosity=0.1
UNET D2 Smagorinsky Mixing=0.05
UNET D2 BCVolumeCheck=0
UNET D2 Cores=0
UNET D2 SolverType=PARDISO (Direct)
UNET D2 Minimum Iterations= 2147483647
UNET D2 Maximum Iterations= 2147483647
UNET D2 Restart Number= 10
UNET D2 Relaxation Coeff=1.3
UNET D2 SOR Precondition Iterations= 10
UNET D2 ILUT Maximum Fill= 8
UNET D2 ILUT Tolerance=1E-08
UNET D1D2 MaxIter= 0
UNET D1D2 ZTol=0.01
UNET D1D2 QTol=0.1
UNET D1D2 MinQTol=1
DSS File=dss
Write IC File= 0
Write IC File at Fixed DateTime=0
Write IC File at Sim End=0
Echo Input=False
Echo Parameters=False
Echo Output=False
Write Detailed= 0
HDF Write Warmup=0
HDF Write Time Slices=0
HDF Flush=0
HDF Compression= 1
HDF Chunk Size= 1
HDF Spatial Parts= 1
HDF Use Max Rows=0
HDF Fixed Rows= 1
Calibration Method= 0
Calibration Iterations= 20
Calibration Max Change=0.05
Calibration Tolerance=0.2
Calibration Maximum=1.5
Calibration Minimum=0.5
Calibration Optimization Method= 1
WQ AD Non Conservative
WQ ULTIMATE=-1
WQ Max Comp Step=1HOUR
WQ Output Interval=15MIN
WQ Output Selected Increments= 0
WQ Output face flow=0
WQ Output face velocity=0
WQ Output face area=0
WQ Output face dispersion=0
WQ Output cell volume=0
WQ Output cell surface area=0
WQ Output cell continuity=0
WQ Output cumulative cell continuity=0
WQ Output face conc=0
WQ Output face dconc_dx=0
WQ Output face courant=0
WQ Output face peclet=0
WQ Output face adv mass=0
WQ Output face disp mass=0
WQ Output cell mass=0
WQ Output cell source sink temp=0
WQ Output nsm pathways=0
WQ Output nsm derived pathways=0
WQ Create Restart=0
WQ Fixed Restart=0
WQ System Summary=0
WQ Write To DSS=0
Sorting and Armoring Iterations= 10
XS Update Threshold= 0.02
Bed Roughness Predictor= 0
Hydraulics Update Threshold= 0.02
Energy Slope Method= 1
Volume Change Method= 1
Sediment Retention Method= 0
Sediment TS Multiplier= 1
Warm Up Method= 0
XS Weighting Method= 0
Number of US Weighted Cross Sections= 1
Number of DS Weighted Cross Sections= 1
Upstream XS Weight=0
Main XS Weight=1
Downstream XS Weight=0
Number of DS XS's Weighted with US Boundary= 1
Upstream Boundary Weight= 1
Weight of XSs Associated with US Boundary= 0
Number of US XS's Weighted with DS Boundary= 1
Downstream Boundary Weight= 0.5
Weight of XSs Associated with DS Boundary= 0.5
Percentile Method= 0
Sediment Output Level= 3
Mass or Volume Output= 0
Output Increment Type= 1
Profile and TS Output Increment= 1
Transport Output Increment 1
XS Output Flag= 0
XS Output Increment= 10
Read HDF5 Sediment Hotstart= 0
Sediment Hotstart Type= 0
Write Gradation File= 0
Read Gradation Hotstart= 0
Write HDF5 File= 1
Write Binary Output= 1
Write DSS Sediment File= 0
DSS Sediment Output Type= 1
SV Curve= 0
Specific Gage Flag= 0
Subcell Erosion Methods= 0
Subcell Deposition Methods= 0
Advection Scheme= 1
Matrix Solver= 0
Implicit Weighting Factor= 1
Maximum Outer Loop Convergence Iterations= 5
Convergence Maximum Absolute= 0.001
Convergence RMSE= 0.0001
Grain Fractions Max Abs Error= 0.001
Max Subgrid Regions= 1
Max Subgrid Length Scale= 3.402823E+38
Initial Layer Thickness= 3.402823E+38
Min Layer Thickness= 3.402823E+38
Max Layer Thickness= 3.402823E+38
Number of Layers= 5

--- TMBLNGRCKRN.f01 (steady flow) ---

Flow Title=Flow
Program Version=6.00
Number of Profiles= 6
Profile Names=01pct,10pct,04pct,02pct,0_2pct,01plus
River Rch & RM=TMBLNGRCKRN,Main,5162
     690     367     487     585     961    1020
Boundary for River Rch & Prof#=TMBLNGRCKRN,Main            , 1
Up Type= 0
Dn Type= 3
Dn Slope=0.03657
Boundary for River Rch & Prof#=TMBLNGRCKRN,Main            , 2
Up Type= 0
Dn Type= 3
Dn Slope=0.03657
Boundary for River Rch & Prof#=TMBLNGRCKRN,Main            , 3
Up Type= 0
Dn Type= 3
Dn Slope=0.03657
Boundary for River Rch & Prof#=TMBLNGRCKRN,Main            , 4
Up Type= 0
Dn Type= 3
Dn Slope=0.03657
Boundary for River Rch & Prof#=TMBLNGRCKRN,Main            , 5
Up Type= 0
Dn Type= 3
Dn Slope=0.03657
Boundary for River Rch & Prof#=TMBLNGRCKRN,Main            , 6
Up Type= 0
Dn Type= 3
Dn Slope=0.03657
DSS Import GetInterval= 0
DSS Import GetPeak= 0
DSS Import FillOption= 0

--- TMBLNGRCKRN.g01 (geometry) ---

Geom Title=Geometry
Program Version=6.10

River Reach=TMBLNGRCKRN     ,Main
Reach XY= 30
     2159798.801      466401.978     2159767.872      466293.044
     2159688.743      466202.274       2159836.4       465874.43
     2159839.429      465764.591     2159809.176      465706.892
     2159675.478      465660.314        2159525.      465537.573
     2159560.796      465364.004     2159548.285      465213.136
      2159456.48      464963.788     2159326.773      464897.131
     2159061.978      464995.374     2158780.734      464843.443
     2158630.674      464802.416     2158581.735      464821.903
     2158571.528      464873.226     2158474.782      464909.415
      2158358.07      464890.374     2158287.845      464781.007
     2158255.774      464517.644     2158096.047      464247.055
     2157880.944      464211.565     2157808.869      464169.261
      2157794.34      464101.167     2157484.533      463991.139
2157366.41744459463828.589403607     2157219.148      463839.975
     2157176.259      463781.841     2157134.932      463481.784

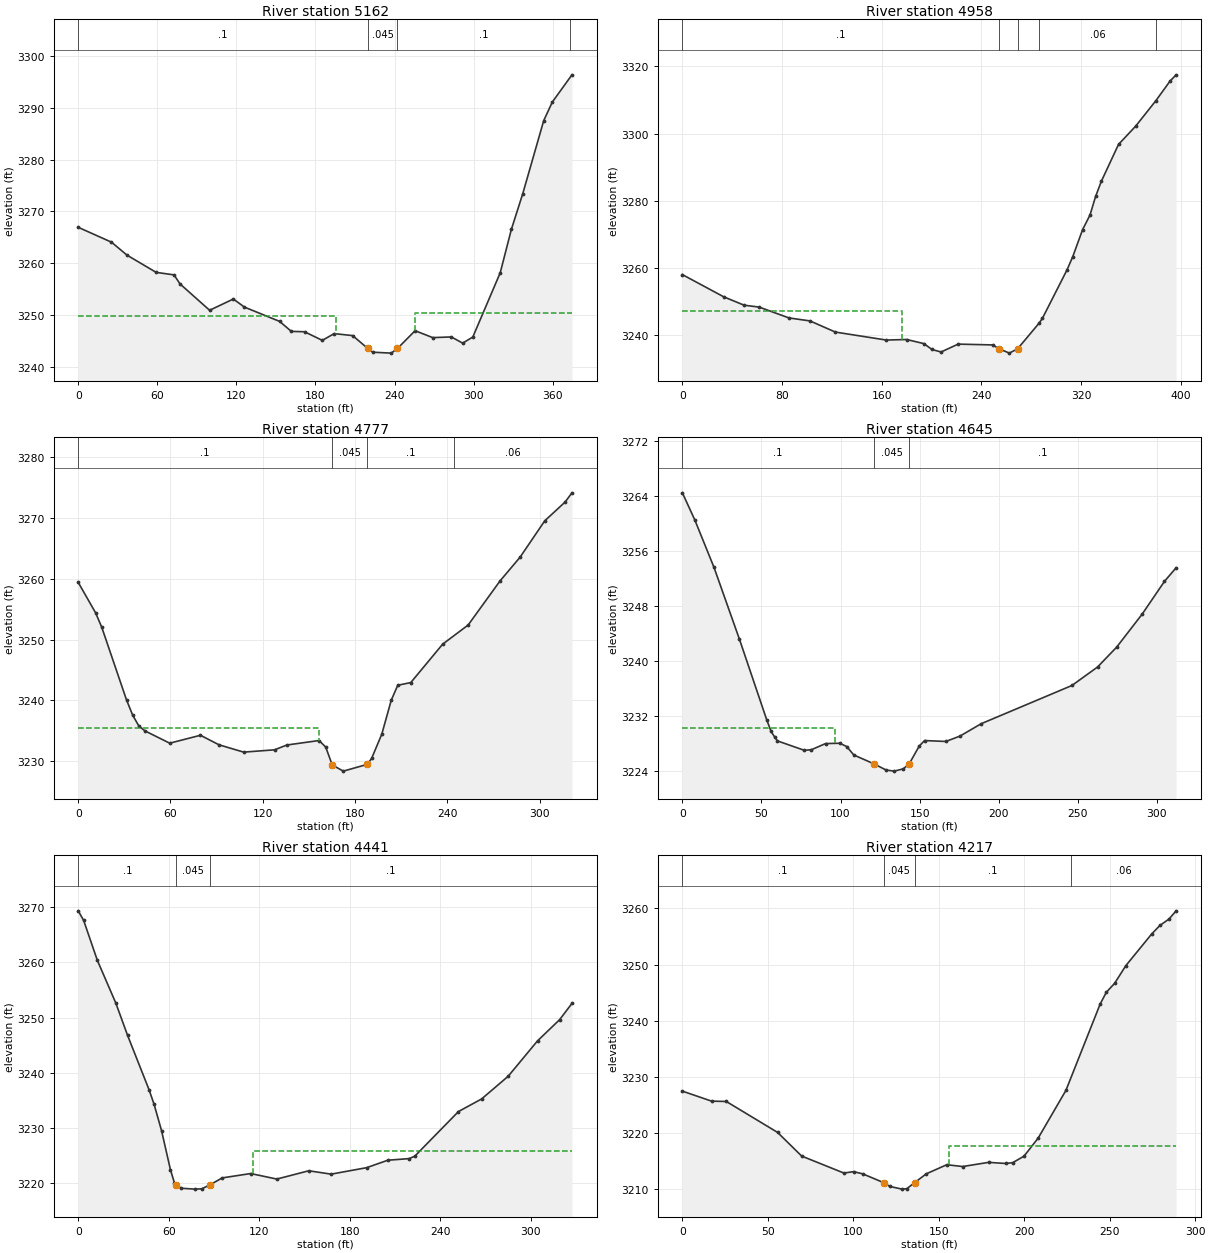
Type RM Length L Ch R = 1 ,5162    ,199.6,204.2,206.1
XS GIS Cut Line= 4
2160004.70797669466279.7925704712159823.35060318466373.598108494
2159752.99644966466428.3180056732159688.89599868466478.347625952
#Sta/Elev= 30
       0 3266.95    25.2 3264.09      37 3261.59    59.1 3258.27    72.7 3257.78
    77.2 3256.05    99.7 3250.96   117.7 3253.13   126.1 3251.57   152.8 3248.82
   161.7 3246.89   171.7 3246.82   185.2 3245.16   194.2 3246.46   208.2 3246.08
   219.7  3243.6   223.4 3242.88   237.5  3242.7  242.25  3243.6   255.6 3247.02
     269 3245.69   283.1 3245.82   291.7 3244.63   299.4  3245.8   320.2 3258.19
   328.7 3266.59   337.3 3273.43   353.2 3287.51   359.7 3291.08374.6234 3296.34
#Mann= 4 ,-1,0
       0      .1       0   219.7    .045       0  242.25      .1       0
  373.31     .06       0
#XS Ineff= 2 , 0
          195.38 3249.91  255.67         3250.45
Permanent Ineff=
       F       F
Bank Sta=219.7,242.25
XS Rating Curve= 0 ,0
Exp/Cntr(USF)=0,0
Exp/Cntr=0.3,0.1

Type RM Length L Ch R = 1 ,4958    ,166.4,181,194.1
XS GIS Cut Line= 3
2159944.76326302466221.964977988  2159769.487964466188.125335869
2159580.00096623466295.234844542
#Sta/Elev= 30
       0 3258.08    33.2 3251.47    49.5 3248.99    61.7 3248.41    85.6 3245.19
   102.4 3244.31   122.8 3240.99   163.6 3238.62     180 3238.78   193.8 3237.56
   200.3 3235.81   207.6 3235.07   221.3 3237.41   248.9 3237.17254.04933236.052
   262.4 3234.73  269.12 3236.06   286.3 3243.66   288.9 3245.07   308.7 3259.51
   313.3 3263.45   321.2 3271.48   327.1 3275.79   331.6 3281.31   336.2 3285.83
     350  3296.8   363.8 3302.25   379.9 3309.77   391.4 3315.66   396.2 3317.49
#Mann= 5 ,-1,0
       0      .1       0254.0493    .045       0  269.12      .1       0
   286.3     .06       0   379.9      .1       0
#XS Ineff= 2 , 0
          176.02 3247.27
Permanent Ineff=
       F       F
Bank Sta=254.0493,269.12
XS Rating Curve= 0 ,0
Exp/Cntr(USF)=0,0
Exp/Cntr=0.3,0.1

Type RM Length L Ch R = 1 ,4777    ,129.9,132.3,134.6
XS GIS Cut Line= 4
2159923.46590899466067.4660032392159782.75760195466078.722667801
2159713.81053151466053.3951725352159611.09346737466081.536833942
#Sta/Elev= 30
       0 3259.39    11.3 3254.39    15.3 3252.02    31.4 3240.09    35.4 3237.59
    39.4 3235.81    43.4    3235    59.5 3232.98    79.5 3234.28    91.6 3232.71
   107.6 3231.51   127.7 3231.89   135.7 3232.68   156.7 3233.42     161 3232.32
   165.2  3229.4   172.4 3228.39     188  3229.5   190.8 3230.47   197.4 3234.44
   203.6 3240.05   207.8 3242.49   216.3 3242.94     237 3249.24   253.6 3252.39
   274.3 3259.62   287.4 3263.54   303.4  3269.5   316.7  3272.6   321.1  3274.1
#Mann= 4 ,-1,0
       0      .1       0   165.2    .045       0     188      .1       0
  244.61     .06       0
#XS Ineff= 2 , 0
          156.71 3235.55
Permanent Ineff=
       F       F
Bank Sta=165.2,188
XS Rating Curve= 0 ,0
Exp/Cntr(USF)=0,0
Exp/Cntr=0.3,0.1

Type RM Length L Ch R = 1 ,4645    ,224.4,203.2,184.2
XS GIS Cut Line= 4
2159928.10012063  465979.61484882159860.87281838465974.924571899
2159745.17932149465917.0778234522159631.04925023465934.275505422
#Sta/Elev= 30
       0 3264.52     7.9 3260.55      20 3253.66    36.1 3243.19    53.3 3231.49
    56.1 3229.77    58.4 3228.95    60.1  3228.4    77.1 3227.03    81.6 3227.12
    90.5 3228.01    99.5 3228.06   103.9 3227.58   108.4 3226.35  120.883225.085
   128.8 3224.16   133.9    3224   139.7 3224.33  143.483225.085   149.7 3227.63
   153.1 3228.45   166.6 3228.32   175.5  3229.1   188.9  3230.9   246.3 3236.47
   262.5 3239.16   274.6 3242.06   290.8 3246.89   304.8 3251.63312.1585 3253.61
#Mann= 3 ,-1,0
       0      .1       0  120.88    .045       0  143.48      .1       0
#XS Ineff= 2 , 0
           96.64 3230.23
Permanent Ineff=
       F       F
Bank Sta=120.88,143.48
XS Rating Curve= 0 ,0
Exp/Cntr(USF)=0,0
Exp/Cntr=0.3,0.1

Type RM Length L Ch R = 1 ,4441    ,232.6,224.5,216.5
XS GIS Cut Line= 4
2159906.21216176465718.5227679712159859.30939275465738.847301209
2159752.99644966465795.1306240232159620.10527079465876.428756975
#Sta/Elev= 30
       0 3269.33     3.6 3267.59    12.7 3260.35    24.9 3252.65    32.7  3246.8
    46.9 3236.99    50.2 3234.39    55.2 3229.58    61.1  3222.5    63.7 3220.15
   65.033219.785    68.2 3219.14    77.3 3218.98    81.8 3219.03   87.513219.784
    95.4 3221.01   114.3  3221.8   131.6  3220.8   152.8  3222.3   167.6 3221.69
   191.1 3222.86   205.2 3224.21   219.3  3224.5     223 3224.93     252 3233.02
   267.3 3235.29   284.9 3239.39   304.4 3245.81     319 3249.63 327.196 3252.58
#Mann= 3 ,-1,0
       0      .1       0   65.03    .045       0   87.51      .1       0
#XS Ineff= 2 , 0
                           115.9         3225.91
Permanent Ineff=
       F       F
Bank Sta=65.03,87.51
XS Rating Curve= 0 ,0
Exp/Cntr(USF)=0,0
Exp/Cntr=0.3,0.1

Type RM Length L Ch R = 1 ,4217    ,183.4,191.7,199.5
XS GIS Cut Line= 4
2159756.12330093465571.5607584032159695.14970121465595.012142908
2159627.92239896 465671.619998962159554.44139418 465768.55238825
#Sta/Elev= 30
       0 3227.48    17.1  3225.7    25.7 3225.64    55.7 3220.14    69.8 3215.93
    94.5 3212.91   100.2 3213.16   105.5 3212.77   117.93211.188   121.4 3210.53
   128.5 3210.05   131.3 3210.12  135.833211.187   142.7 3212.77   154.7 3214.39
     164 3214.07   179.2 3214.81   189.3 3214.61   193.3 3214.76   199.9 3215.91
   208.2 3219.14   224.4  3227.6   244.5 3243.01   248.1 3245.08   252.9 3246.65
   259.5 3249.81   274.6 3255.43   279.4 3256.95   284.7 3258.08 288.887 3259.55
#Mann= 4 ,-1,0
       0      .1       0   117.9    .045       0  135.83      .1       0
  227.25     .06       0
#XS Ineff= 2 , 0
                          155.78         3217.73
Permanent Ineff=
       F       F
Bank Sta=117.9,135.83
XS Rating Curve= 0 ,0
Exp/Cntr(USF)=0,0
Exp/Cntr=0.3,0.1

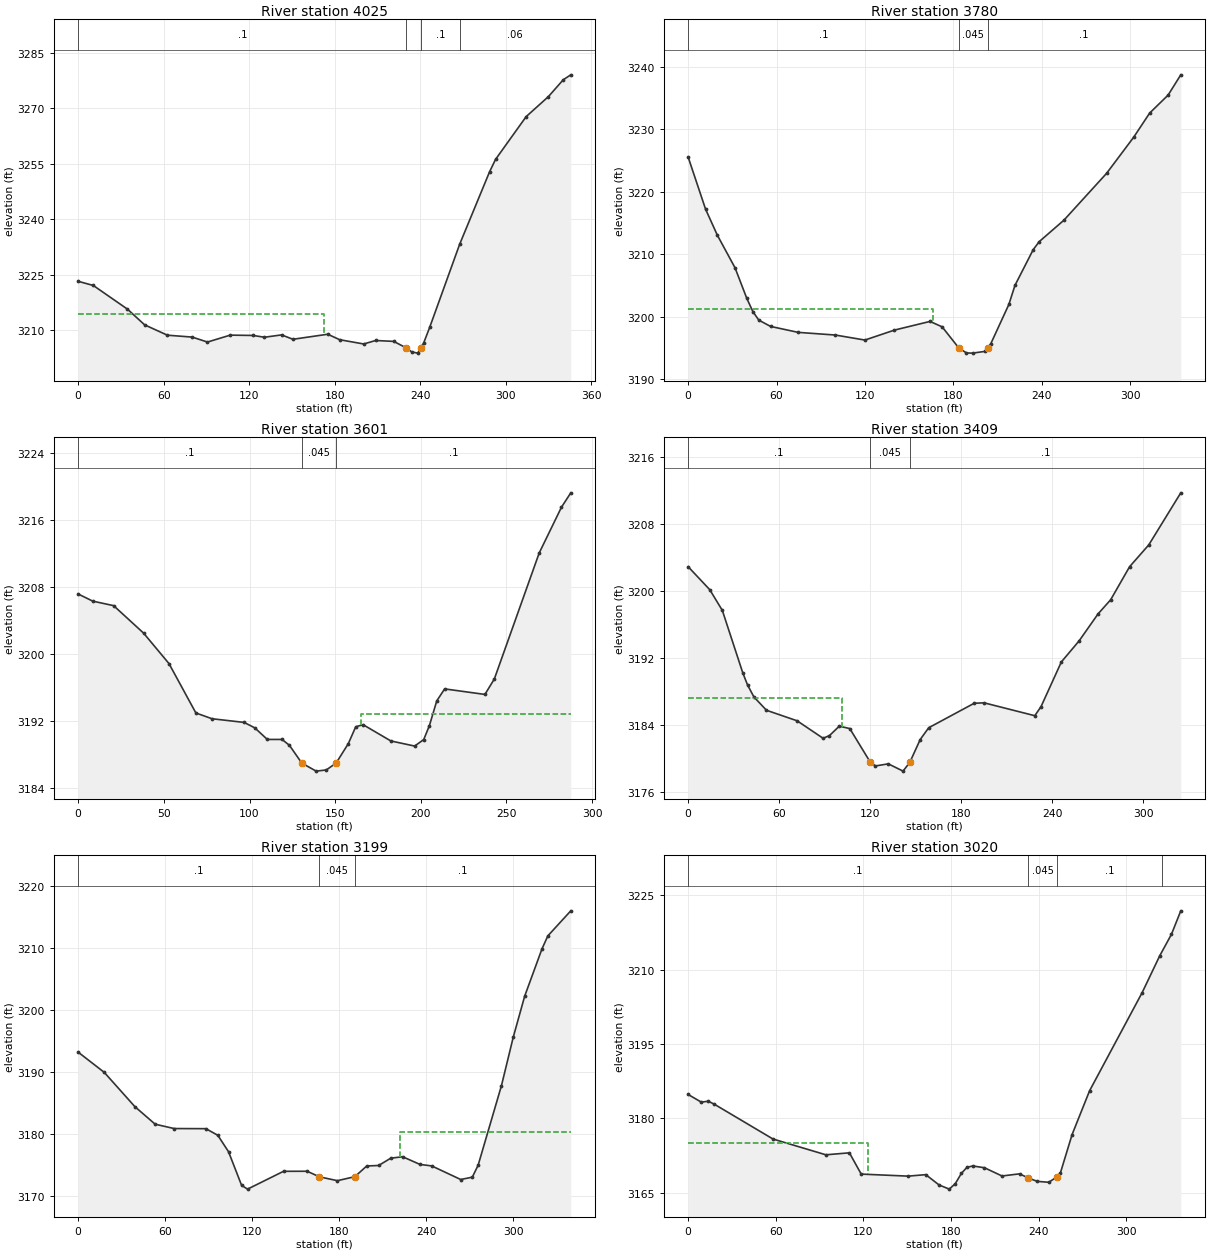
Type RM Length L Ch R = 1 ,4025    ,246.7,245.3,244.6
XS GIS Cut Line= 4
 2159750.7404736465502.2664675012159583.35203091465494.394239643
2159460.63585616465534.0385431942159415.29651278465552.799650798
#Sta/Elev= 30
       0 3223.23    10.6 3222.11    34.6 3215.71    46.6 3211.48    62.6 3208.68
      80 3208.17    90.7 3206.83   106.7  3208.7   122.7 3208.61   130.7 3208.13
   142.7 3208.76   150.7 3207.58   175.1 3208.94   183.5 3207.46   200.3 3206.31
   208.7 3207.25   221.4 3207.01   230.3 3205.22     234 3204.17   238.2 3203.84
240.56453205.307   242.4 3206.59   246.6 3210.79   267.6  3233.2   288.6 3252.78
   292.8 3256.14   314.3  3267.7   329.9  3273.1   340.3 3277.64   345.6 3278.98
#Mann= 4 ,-1,0
       0      .1       0   230.3    .045       0240.5645      .1       0
  267.57     .06       0
#XS Ineff= 2 , 0
          172.34 3214.37
Permanent Ineff=
       F       F
Bank Sta=230.3,240.5645
XS Rating Curve= 0 ,0
Exp/Cntr(USF)=0,0
Exp/Cntr=0.3,0.1

Type RM Length L Ch R = 1 ,3780    ,181,178.6,175.7
XS GIS Cut Line= 4
2159748.00861873465269.8376003262159590.02697425465274.212333966
2159493.46779446465297.9612725042159419.98678968465319.849231376
#Sta/Elev= 30
       0 3225.52    11.8 3217.21    19.8 3213.04    31.8 3207.83    39.8 3202.93
    43.9 3200.83    47.9 3199.47    55.9 3198.46    74.6 3197.51    99.9 3197.08
   119.9 3196.28   139.9 3197.87   164.1 3199.26   172.3 3198.39183.57633195.028
   188.8 3194.22   192.9 3194.19   201.1 3194.46203.14633195.035   205.3 3195.69
   217.6 3201.99   221.7 3205.02   234.1 3210.74   238.2 3212.02   254.9 3215.44
   283.9 3222.94   302.2 3228.69   313.1 3232.57   325.6 3235.44   334.2 3238.68
#Mann= 3 ,-1,0
       0      .1       0183.5763    .045       0203.1463      .1       0
#XS Ineff= 2 , 0
          165.95 3201.21
Permanent Ineff=
       F       F
Bank Sta=183.5763,203.1463
XS Rating Curve= 0 ,0
Exp/Cntr(USF)=0,0
Exp/Cntr=0.3,0.1

Type RM Length L Ch R = 1 ,3601    ,199,192.6,180.7
XS GIS Cut Line= 4
 2159648.2469322465061.8840018152159562.25852235465091.589088855
2159451.25530235465135.3650065992159385.59142574465176.014073075
#Sta/Elev= 30
       0 3207.17     8.5 3206.32    20.7 3205.78    38.2  3202.5      53 3198.87
    68.7 3192.98    78.1 3192.29    96.9 3191.85   103.1  3191.2   110.4 3189.82
     119 3189.82   123.3 3189.12  130.533186.998   138.9 3186.04   144.8 3186.18
  150.563186.999   157.7 3189.33     162 3191.33   166.3 3191.58   182.5 3189.64
   196.4 3189.03   201.7 3189.81     205 3191.47   209.3 3194.42   213.9 3195.85
   237.4 3195.19   242.9 3197.03   269.1 3212.07   282.1 3217.53287.5255 3219.24
#Mann= 3 ,-1,0
       0      .1       0  130.53    .045       0  150.56      .1       0
#XS Ineff= 2 , 0
                          165.02          3192.8
Permanent Ineff=
       F       F
Bank Sta=130.53,150.56
XS Rating Curve= 0 ,0
Exp/Cntr(USF)=0,0
Exp/Cntr=0.3,0.1

Type RM Length L Ch R = 1 ,3409    ,227.6,209.3,181.1
XS GIS Cut Line= 4
2159545.85276388464898.5196236072159449.95548113464925.126539228
 2159384.1961761464990.6914327822159346.54802405465117.470131328
#Sta/Elev= 30
       0 3202.93    14.2 3200.19    22.5 3197.71      36 3190.23    39.1  3188.8
    43.3 3187.36    51.6 3185.76    71.8  3184.5    88.9 3182.41    93.1 3182.73
    99.6 3183.86   106.5 3183.57  119.93 3179.57   123.4  3179.1   131.9 3179.35
   141.6 3178.48   146.1 3179.55   152.9 3182.26   158.5 3183.67   188.5  3186.6
     195 3186.65   228.4 3185.11   232.5 3186.19   245.9 3191.54   257.6 3194.06
   270.1 3197.29   278.4 3198.98   290.9 3202.94   303.5 3205.54   324.6 3211.77
#Mann= 3 ,0,0
       0      .1       0  119.93    .045       0   146.1      .1       0
#XS Ineff= 2 , 0
          101.55 3187.21
Permanent Ineff=
       F       F
Bank Sta=119.93,146.1
XS Rating Curve= 0 ,0
Exp/Cntr(USF)=0,0
Exp/Cntr=0.3,0.1

Type RM Length L Ch R = 1 ,3199    ,175.3,179.1,184.9
XS GIS Cut Line= 4
2159255.40675262464760.7386243892159219.66546173464840.703601034
2159251.17062905464974.7927049792159258.58844885465088.895353755
#Sta/Elev= 30
       0 3193.22      18 3189.96    39.1 3184.44    53.1 3181.61    66.2 3180.91
    88.1 3180.89    96.3 3179.82   103.7 3177.17   112.7 3171.76   116.8 3171.15
   141.6 3174.02   157.9 3174.03166.3759 3173.13   178.8 3172.51   190.8 3173.16
     199 3174.88   207.2 3174.96   215.5 3176.13   223.7 3176.37   235.7 3175.13
   243.8 3174.89   263.8  3172.7   271.8 3173.08   275.8    3175   291.9 3187.83
     300 3195.61   307.9 3202.24   319.9  3209.9   323.9 3211.96   339.7 3215.99
#Mann= 3 ,0,0
       0      .1       0166.3759    .045       0   190.8      .1       0
#XS Ineff= 2 , 0
                          222.23         3180.43
Permanent Ineff=
       F       F
Bank Sta=166.3759,190.8
XS Rating Curve= 0 ,0
Exp/Cntr(USF)=0,0
Exp/Cntr=0.3,0.1

Type RM Length L Ch R = 1 ,3020    ,194.4,201.3,207.5
XS GIS Cut Line= 4
 2159096.3576835464755.4525776092159076.03315026464936.809951118
  2159072.906299465038.432617309  2159072.906299465091.589088855
#Sta/Elev= 30
       0 3184.84       9  3183.3    13.8 3183.48    17.8  3182.9    58.1 3175.86
    94.3 3172.68   110.4 3173.08   118.5 3168.79   150.7 3168.38   162.7 3168.68
   171.8  3166.6   178.8 3165.76   182.9 3166.86   187.1 3168.94   190.9 3170.16
   194.9 3170.43   202.9 3170.07   214.9 3168.41   226.9 3168.84   232.6 3168.06
   238.9 3167.33   246.9 3167.14   252.6 3168.24   254.9 3169.04   262.9 3176.77
   274.9 3185.61   310.9  3205.4   322.9  3212.8   330.9 3217.12337.3199 3221.87
#Mann= 4 ,-1,0
       0      .1       0   232.6    .045       0   252.6      .1       0
  324.16     .06       0
#XS Ineff= 2 , 0
          123.17 3175.06
Permanent Ineff=
       F       F
Bank Sta=232.6,252.6
XS Rating Curve= 0 ,0
Exp/Cntr(USF)=0,0
Exp/Cntr=0.3,0.1

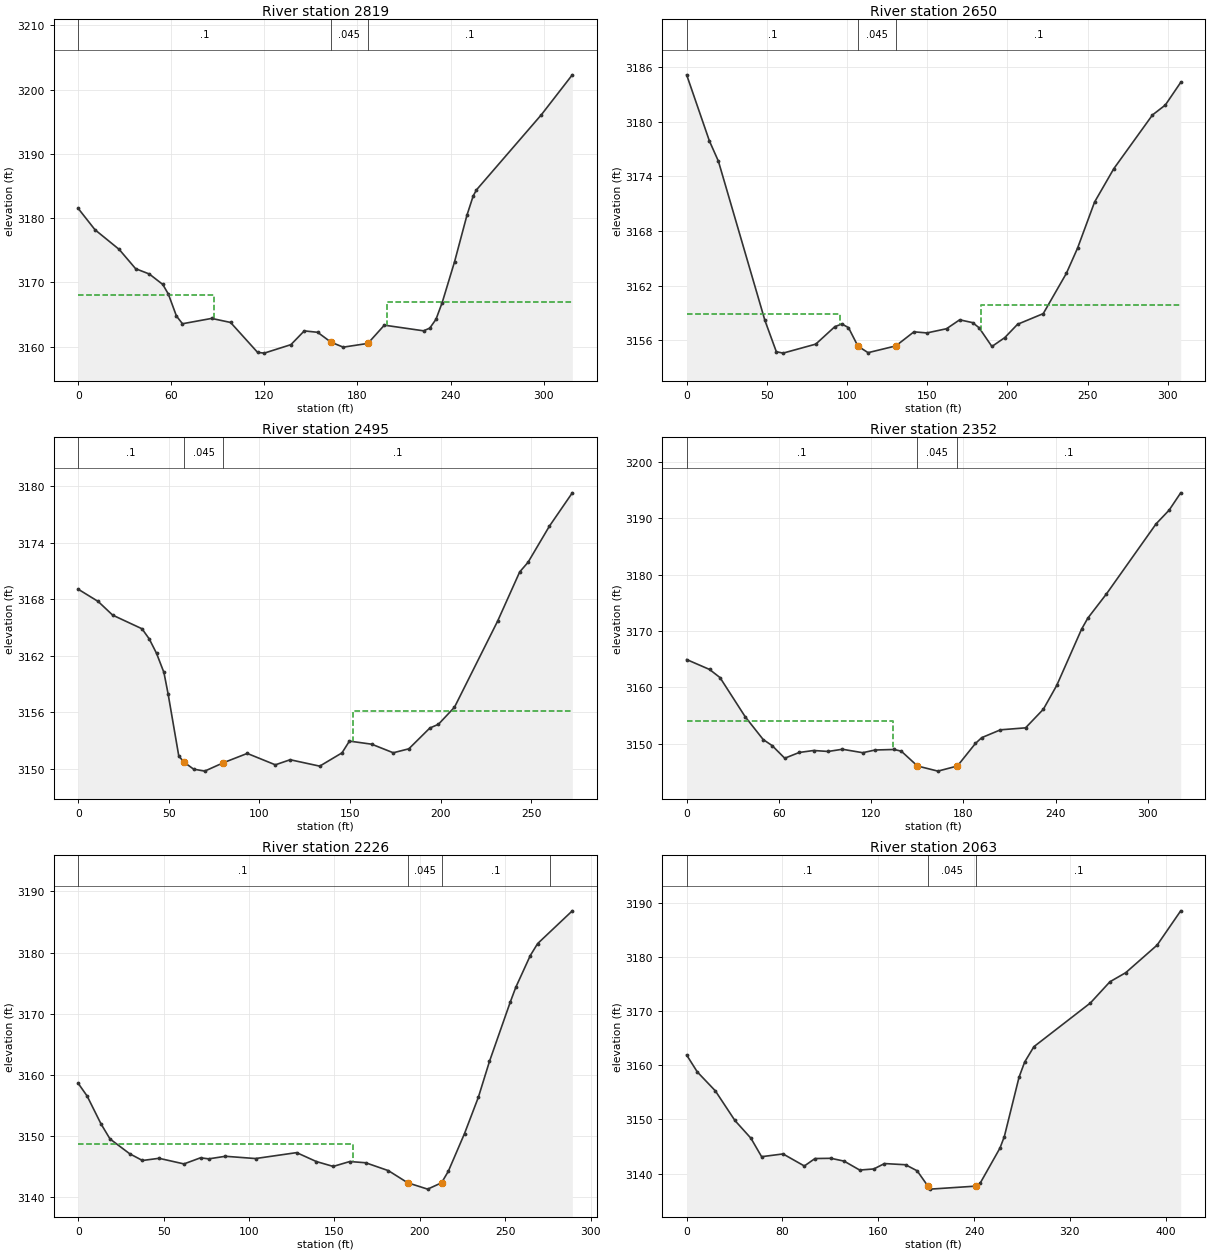
Type RM Length L Ch R = 1 ,2819    ,172.6,168.6,164.8
XS GIS Cut Line= 4
2158958.77622774464763.2697057772158913.43688436464866.455797602
2158875.91466915464961.8247612582158871.22439225465065.010853082
#Sta/Elev= 30
       0 3181.51    10.8  3178.2    26.4 3175.14      37 3172.14    45.8 3171.32
    54.5 3169.69    58.1 3168.19    63.3 3164.78    67.2 3163.58      86 3164.41
    98.2 3163.78   115.6 3159.13   119.9 3159.01   137.1 3160.33   145.7 3162.47
   154.3 3162.25   162.9 3160.72   170.8 3159.94   186.7 3160.52   197.3 3163.36
   222.6 3162.48   226.6  3162.9   230.6 3164.27   234.6 3166.87   242.6 3173.24
   250.6 3180.49   254.6 3183.47   256.7  3184.4   298.6 3196.11318.4852  3202.3
#Mann= 3 ,-1,0
       0      .1       0   162.9    .045       0   186.7      .1       0
#XS Ineff= 2 , 0
           87.24 3168.08  199.06         3166.91
Permanent Ineff=
       F       F
Bank Sta=162.9,186.7
XS Rating Curve= 0 ,0
Exp/Cntr(USF)=0,0
Exp/Cntr=0.3,0.1

Type RM Length L Ch R = 1 ,2650    ,163.2,155,146.3
XS GIS Cut Line= 4
2158778.98227986464719.4937880332158761.78459789464778.903962114
2158740.00418547464888.5066769942158745.44808794465022.798360972
#Sta/Elev= 30
       0 3185.17    14.2  3177.9    19.8 3175.68    48.8 3158.18    55.9 3154.75
    60.1 3154.59    80.5 3155.58    92.4  3157.5    96.8 3157.79   100.9 3157.39
  106.77 3155.36   113.1 3154.64130.39953155.382   141.7 3156.93   149.8 3156.81
     162 3157.27   170.2 3158.25   178.3 3157.94   182.3 3157.38   190.3 3155.32
   198.3 3156.29   206.3 3157.76   222.3 3158.93   236.7 3163.35   243.7 3166.13
   254.3 3171.19   266.3 3174.86   290.4 3180.76   298.4 3181.85     308 3184.34
#Mann= 3 ,0,0
       0      .1       0  106.77    .045       0130.3995      .1       0
#XS Ineff= 2 , 0
           95.87 3158.85  183.72         3159.92
Permanent Ineff=
       F       F
Bank Sta=106.77,130.3995
XS Rating Curve= 0 ,0
Exp/Cntr(USF)=0,0
Exp/Cntr=0.3,0.1

Type RM Length L Ch R = 1 ,2495    ,141.6,143.4,144.9
XS GIS Cut Line= 4
2158591.37120382464738.2548956382158596.06148072464778.903962114
2158627.32999339464921.1756947812158644.52767536465005.600679001
#Sta/Elev= 30
       0 3169.08      11 3167.78      19 3166.33    35.2 3164.88    39.2  3163.8
    43.2 3162.28    47.3 3160.24    49.6 3157.97    55.5 3151.37   58.353150.717
    63.7 3149.97    69.8 3149.76    80.1 3150.65    93.3 3151.64   108.8 3150.43
     117 3150.97   133.3 3150.29   145.6  3151.7   149.7 3152.95     162 3152.62
   173.9 3151.71   182.5 3152.13   194.1 3154.34   198.8 3154.73   207.7 3156.55
   231.5 3165.69   243.7 3170.92   248.3 3171.94   260.1 3175.78272.7449 3179.32
#Mann= 3 ,-1,0
       0      .1       0   58.35    .045       0    80.1      .1       0
#XS Ineff= 2 , 0
                          151.49         3156.14
Permanent Ineff=
       F       F
Bank Sta=58.35,80.1
XS Rating Curve= 0 ,0
Exp/Cntr(USF)=0,0
Exp/Cntr=0.3,0.1

Type RM Length L Ch R = 1 ,2352    ,113.5,125.6,138.4
XS GIS Cut Line= 4
2158558.14488022464750.7040936852158501.59073466464843.247240964
2158524.21239288464960.4685608512158537.57973638 465053.01170813
#Sta/Elev= 30
       0 3164.92    14.9 3163.16    21.7 3161.72    38.1 3154.76    49.8 3150.72
    55.6 3149.65    63.8 3147.41    73.2 3148.43    82.6 3148.78      92 3148.61
   101.3    3149   114.5 3148.39   122.6 3148.87   134.9 3148.96   139.6 3148.66
   150.13146.032   163.4 3145.12  176.07 3146.03   187.8 3150.03   191.9 3151.06
   204.1 3152.45   220.4  3152.8     232 3156.11   240.7 3160.34   256.8 3170.29
   260.9 3172.27     273 3176.56   305.3    3189   313.8 3191.44   321.3  3194.5
#Mann= 3 ,0,0
       0      .1       0   150.1    .045       0  176.07      .1       0
#XS Ineff= 2 , 0
          134.48 3153.94
Permanent Ineff=
       F       F
Bank Sta=150.1,176.07
XS Rating Curve= 0 ,0
Exp/Cntr(USF)=0,0
Exp/Cntr=0.3,0.1

Type RM Length L Ch R = 1 ,2226    ,144.5,163.2,181.3
XS GIS Cut Line= 4
2158499.12909143464738.2548956382158405.32355341 464874.27292577
 2158367.8013382464957.1344843572158356.85735876464988.402997031
#Sta/Elev= 30
       0 3158.56     5.2 3156.49    13.3 3151.94    18.6 3149.46    30.1 3147.04
    37.6 3145.93    47.3 3146.29    61.9 3145.37    71.6 3146.37    76.4  3146.2
    86.2 3146.62   103.8 3146.25   127.9 3147.22   139.4 3145.76   149.3 3144.96
     159 3145.76   168.3 3145.56   181.6 3144.27  192.943142.275   204.6 3141.24
  212.743142.276   216.7 3144.16   226.2 3150.35   234.3 3156.29   240.8 3162.16
   252.9 3171.82   256.2 3174.29   264.7  3179.5     269 3181.46 289.318 3186.83
#Mann= 4 ,-1,0
       0      .1       0  192.94    .045       0  212.74      .1       0
  276.19     .06       0
#XS Ineff= 2 , 0
          160.73 3148.71
Permanent Ineff=
       F       F
Bank Sta=192.94,212.74
XS Rating Curve= 0 ,0
Exp/Cntr(USF)=0,0
Exp/Cntr=0.3,0.1

Type RM Length L Ch R = 1 ,2063    ,151.1,153.3,155.5
XS GIS Cut Line= 4
2158492.33641993464697.2347197022158331.92829798464776.410523485
2158217.79174967464805.2017248612158170.49191884464911.112215636
#Sta/Elev= 30
       0 3161.92     8.9 3158.79      24 3155.28    40.3 3149.81    53.7 3146.52
    62.6 3143.11    80.5 3143.62    98.3 3141.39   107.2 3142.77   120.6 3142.81
   131.5 3142.29   144.5 3140.64   156.3 3140.84   165.2 3141.84   182.8 3141.62
   192.5  3140.5  201.55 3137.65   203.4 3137.11   241.9 3137.67   245.2 3138.24
   261.7 3144.72   265.3 3146.83   277.6 3157.82   282.3 3160.63     290 3163.46
   337.2 3171.55   353.5 3175.47   366.7 3177.15   392.9 3182.25   412.6 3188.59
#Mann= 3 ,0,0
       0      .1       0  201.55    .045       0   241.9      .1       0
Bank Sta=201.55,241.9
XS Rating Curve= 0 ,0
Exp/Cntr(USF)=0,0
Exp/Cntr=0.3,0.1

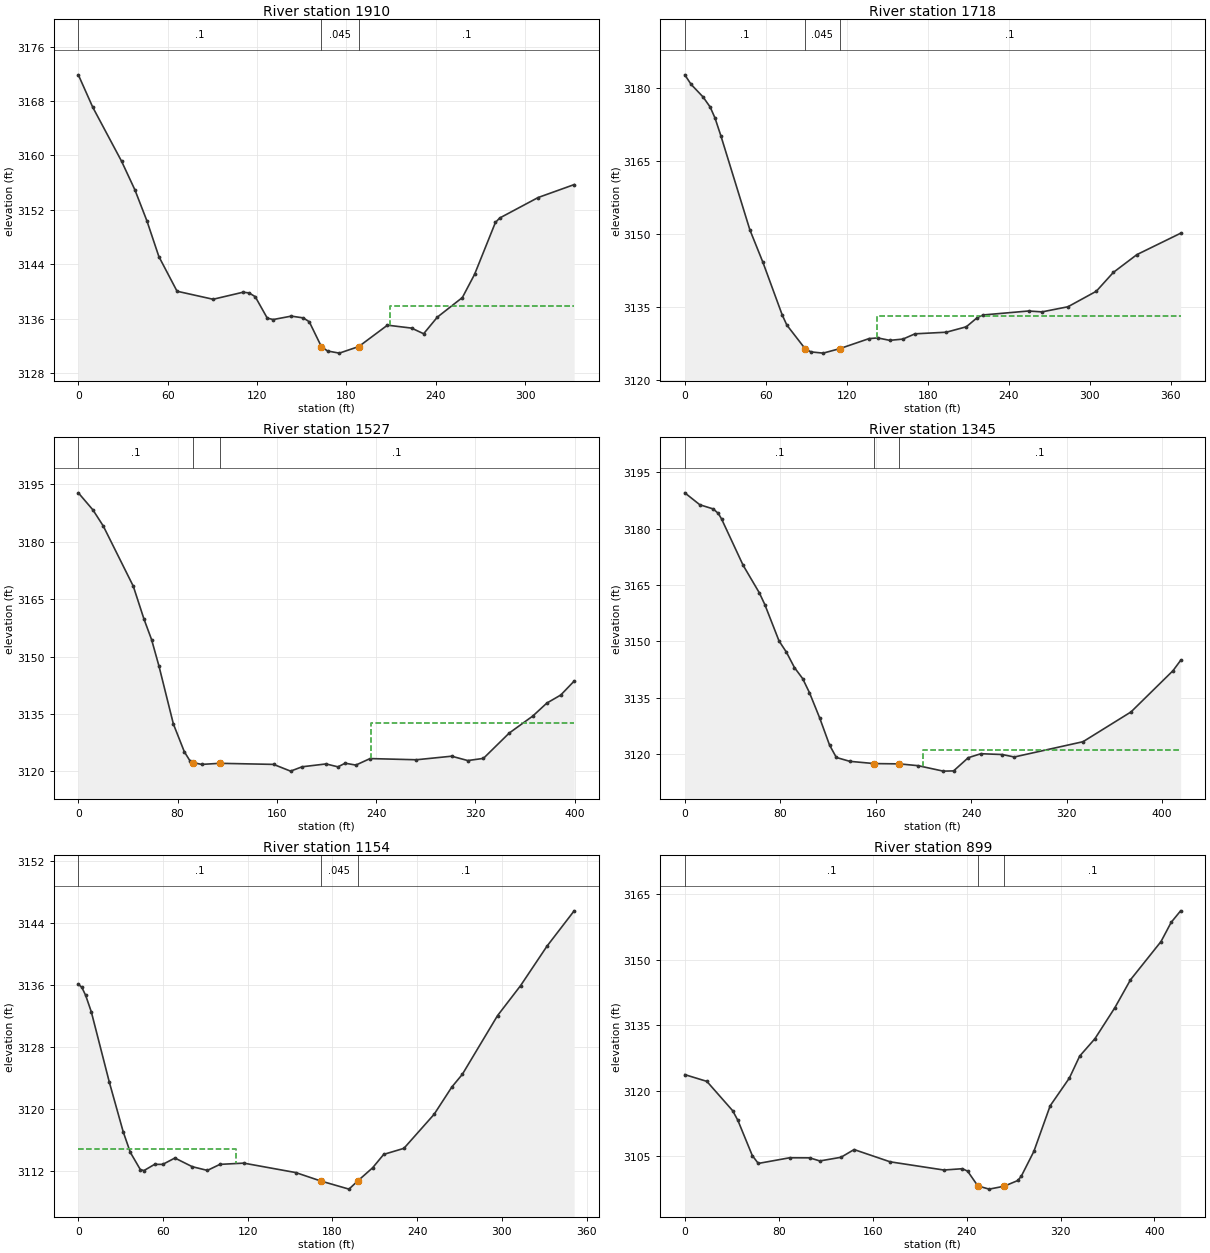
Type RM Length L Ch R = 1 ,1910    ,199.6,192.1,185
XS GIS Cut Line= 4
2158453.78974805464610.0539936742158331.84254862464627.251675645
2158219.27590299464642.8859319822158150.48517511464710.113234231
#Sta/Elev= 30
       0 3171.86     9.7 3167.09      29 3159.17      38 3154.94    46.1 3150.36
    54.1 3145.13    66.3 3140.04    90.5 3138.86   110.7  3139.9   114.7 3139.79
   118.8 3139.24   126.9 3136.08   130.9 3135.88     143 3136.38   151.1 3136.12
   155.1 3135.55   163.2 3131.91   167.4 3131.25   175.3 3130.94  188.343131.909
   207.6 3135.05   223.8 3134.62   231.9 3133.79   241.1 3136.23   257.9 3139.11
   266.1 3142.52   280.1 3150.15     283 3150.81   308.8 3153.82332.9867 3155.72
#Mann= 3 ,-1,0
       0      .1       0   163.2    .045       0  188.34      .1       0
#XS Ineff= 2 , 0
                          209.46          3137.8
Permanent Ineff=
       F       F
Bank Sta=163.2,188.34
XS Rating Curve= 0 ,0
Exp/Cntr(USF)=0,0
Exp/Cntr=0.3,0.1

Type RM Length L Ch R = 1 ,1718    ,193.2,190.8,187.6
XS GIS Cut Line= 4
2158308.39116412464413.0623638272158236.47358497464447.457727769
2158134.85091878464499.0507736812158083.25787286464664.773890854
#Sta/Elev= 30
       0 3182.62     4.7 3180.65    13.5 3178.09    18.8 3176.01    22.4 3173.74
    26.8 3170.05    48.2 3150.82    57.9 3144.14    72.2 3133.34    75.6 3131.29
   89.093126.457    93.5 3125.79   102.5 3125.54  114.743126.457   136.5 3128.52
   142.9 3128.66   151.8 3128.16   161.6 3128.42   170.5  3129.5   193.7 3129.83
   208.5 3130.94   216.7 3132.84   221.1 3133.37   254.6 3134.18   264.6    3134
   283.8 3135.05   304.8 3138.23   317.4 3142.09   334.9 3145.75367.2571 3150.13
#Mann= 3 ,-1,0
       0      .1       0   89.09    .045       0  114.74      .1       0
#XS Ineff= 2 , 0
                          142.13         3133.15
Permanent Ineff=
       F       F
Bank Sta=89.09,114.74
XS Rating Curve= 0 ,0
Exp/Cntr(USF)=0,0
Exp/Cntr=0.3,0.1

Type RM Length L Ch R = 1 ,1527    ,180.8,182.3,176
XS GIS Cut Line= 4
2158214.58562609464239.5221184862158148.92174948464275.480908061
2157995.70603737464378.6669998862157887.82966865464467.782261007
#Sta/Elev= 30
       0  3192.8    11.8 3188.32    20.1 3184.13    44.3 3168.39    52.9 3159.81
      59 3154.47    64.9 3147.63    76.6 3132.39    85.4 3125.16    90.2 3122.65
    92.2 3122.32    99.4 3121.85   114.1 3122.13   157.3 3121.85     171 3120.09
   180.4 3121.23   199.6 3121.97   209.2 3121.21     215 3122.16   223.6 3121.67
   235.1 3123.37   272.4 3123.06   300.8 3123.99   313.8 3122.85   326.4 3123.42
   347.2 3130.04   366.2 3134.49   377.5 3137.87   388.7 3139.97399.5121 3143.62
#Mann= 3 ,-1,0
       0      .1       0    92.2    .045       0   114.1      .1       0
#XS Ineff= 2 , 0
                          235.94         3132.67
Permanent Ineff=
       F       F
Bank Sta=92.2,114.1
XS Rating Curve= 0 ,0
Exp/Cntr(USF)=0,0
Exp/Cntr=0.3,0.1

Type RM Length L Ch R = 1 ,1345    ,187.5,190.5,188.5
XS GIS Cut Line= 4
2158127.30511678464139.9193216432158023.45114038464195.445210011
2157919.59716399464283.875328522  2157791.065015464381.559761761
#Sta/Elev= 30
       0 3189.54    12.6 3186.36    23.9 3185.24    28.1 3184.04    30.8 3182.59
    48.9 3170.23    62.5 3162.88    67.1 3159.75      79 3150.07    85.2 3147.07
    91.9 3142.99    98.8 3140.04   104.5 3136.29     113 3129.61   121.3 3122.36
     127 3119.03   138.3    3118   158.8  3117.4   179.9 3117.32   195.6 3116.84
   216.6 3115.39   225.3 3115.45   237.6 3118.97   248.2 3120.03   266.1 3119.81
   276.2 3119.16   333.8 3123.23     374 3131.16   409.2 3142.15   415.6  3144.9
#Mann= 3 ,0,0
       0      .1       0   158.8    .045       0   179.9      .1       0
#XS Ineff= 2 , 0
                             200            3121
Permanent Ineff=
       F       F
Bank Sta=158.8,179.9
XS Rating Curve= 0 ,0
Exp/Cntr(USF)=0,0
Exp/Cntr=0.3,0.1

Type RM Length L Ch R = 1 ,1154    ,262,255.6,246.1
XS GIS Cut Line= 4
2157958.18382217464051.9110424412157858.12458161464122.265195958
2157770.57274612464206.6901801782157706.47229514464292.678590032
#Sta/Elev= 30
       0 3136.11     2.5 3135.68     5.2 3134.65     9.2 3132.52      22  3123.4
    31.8 3117.01    36.8 3114.37    43.9 3112.14    46.5 3112.01      54 3112.81
    59.8 3112.81    68.4 3113.63    80.7 3112.51    91.4 3112.03   100.3 3112.81
   117.2 3112.97     154 3111.75  171.733110.661   191.7 3109.61  197.873110.661
   208.4 3112.36   216.3  3114.1   230.6 3114.88     252 3119.28   264.6 3122.82
     272 3124.45   296.9 3132.03   313.2  3135.9   331.9    3141 351.195 3145.58
#Mann= 3 ,-1,0
       0      .1       0  171.73    .045       0  197.87      .1       0
#XS Ineff= 2 , 0
             112 3114.74
Permanent Ineff=
       F       F
Bank Sta=171.73,197.87
XS Rating Curve= 0 ,0
Exp/Cntr(USF)=0,0
Exp/Cntr=0.3,0.1

Type RM Length L Ch R = 1 ,899     ,117,123.3,130.8
XS GIS Cut Line= 3
 2157825.9408316463865.7831699912157637.81738827 464009.09167653
2157566.28705396464180.620564011
#Sta/Elev= 30
       0 3123.64    18.8 3122.09    40.8 3115.36    45.2 3113.16    57.5 3105.08
    62.6 3103.28    89.3 3104.58   106.4 3104.56     115 3103.85     133 3104.69
   144.2 3106.46   174.9 3103.65   220.6 3101.77   236.5 3102.07   240.9  3101.5
   249.6 3098.13   259.2 3097.39   271.9 3098.05   283.7 3099.37   286.7 3100.41
   297.3 3106.04   311.2  3116.5   327.6 3122.88   336.3 3127.88   349.3 3131.87
   366.3 3138.99   379.6 3145.38   405.6 3154.15   414.3 3158.57   422.3 3161.19
#Mann= 3 ,0,0
       0      .1       0   249.6    .045       0   271.9      .1       0
Bank Sta=249.6,271.9
XS Rating Curve= 0 ,0
Exp/Cntr(USF)=0,0
Exp/Cntr=0.3,0.1