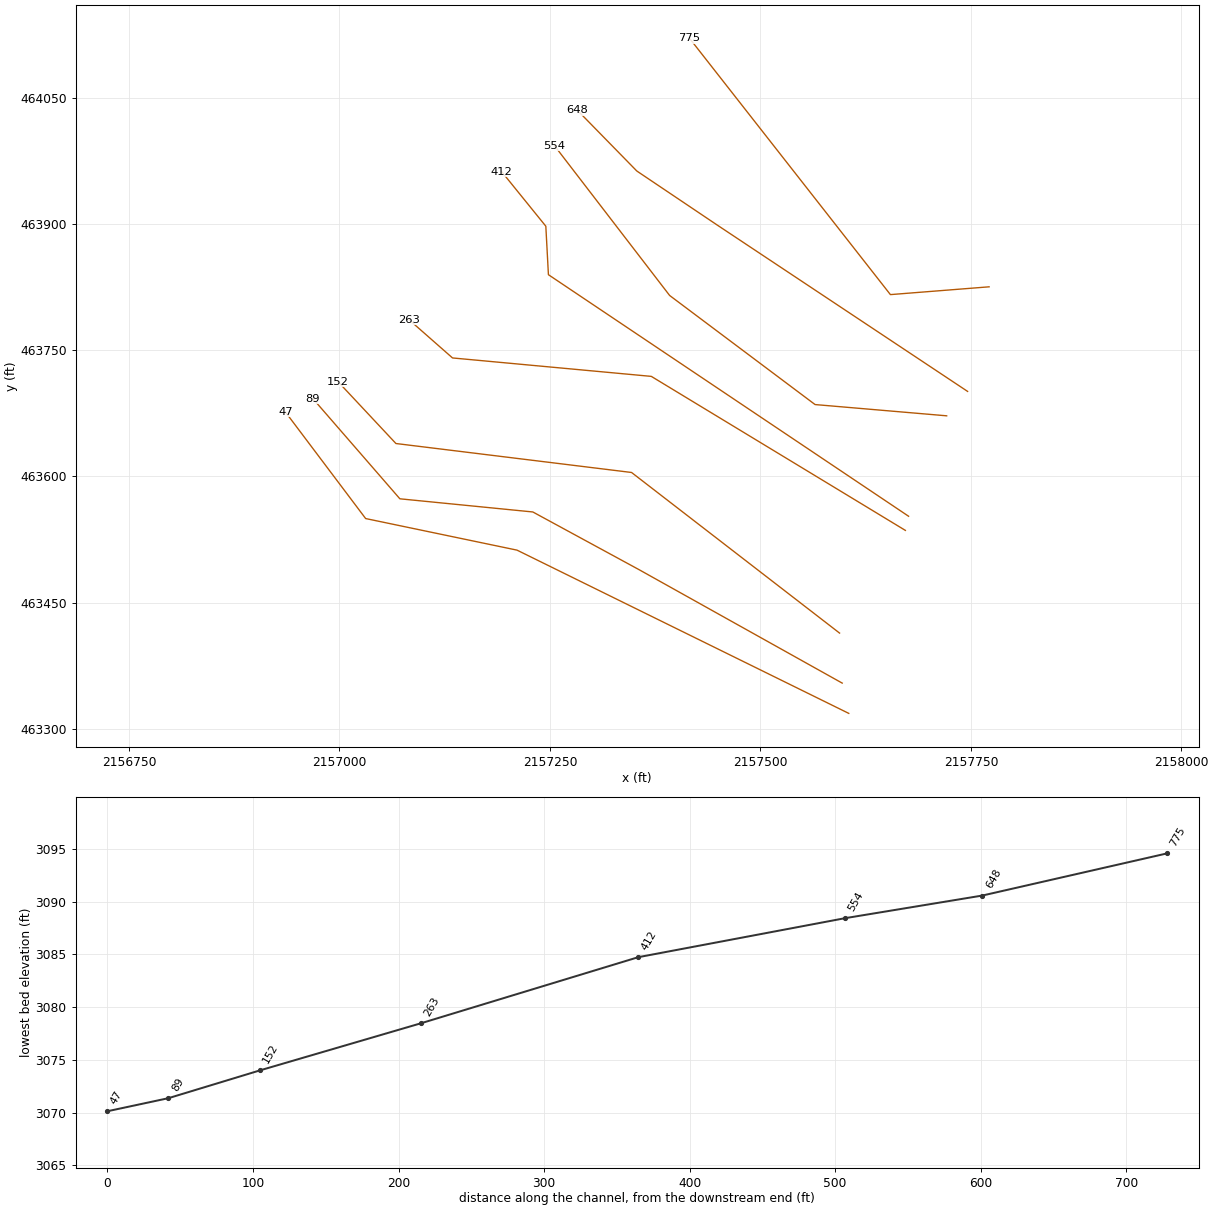
HEC-RAS study TMBLNGRCKRN.prj: TMBLNGRCKRN

--- TMBLNGRCKRN.g01 (geometry) --- (continued)

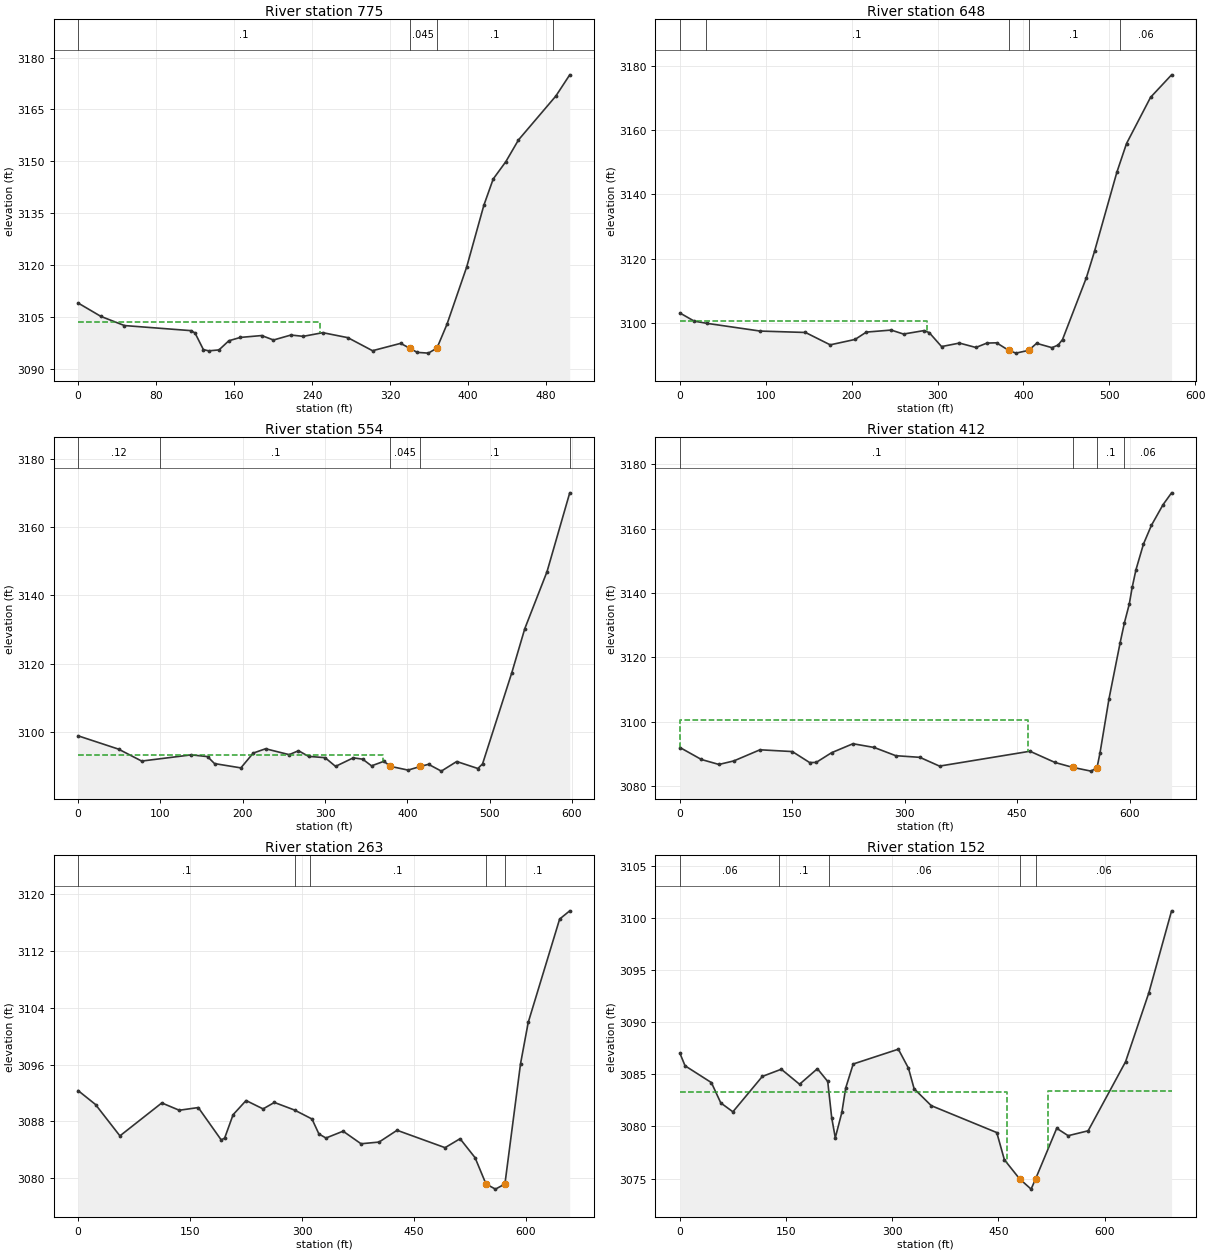
Type RM Length L Ch R = 1 ,775     ,120,126.9,133.3
XS GIS Cut Line= 3
2157771.52812835463825.2726208942157654.30680846463816.018306166
2157415.75113992464120.382434995
#Sta/Elev= 30
       0 3109.07    23.4  3105.2    47.5 3102.56   115.7 3101.09   119.9 3100.42
   128.5 3095.61     134 3095.25   144.5 3095.52   154.6 3098.16   166.4 3099.13
   188.3 3099.67   200.4 3098.38   218.3 3099.82   230.9 3099.44     251  3100.5
   276.7 3099.06     302 3095.29   330.8 3097.41   340.2 3096.01   347.8 3094.81
   359.3 3094.59   368.1 3096.05   378.3 3102.88   398.6 3119.49   416.2 3137.32
   425.8 3144.92   438.8 3149.95   451.7  3156.2   490.1 3168.91   504.3 3175.02
#Mann= 4 ,-1,0
       0      .1       0   340.2    .045       0   368.1      .1       0
  487.59     .06       0
#XS Ineff= 2 , 0
          247.71 3103.73
Permanent Ineff=
       F       F
Bank Sta=340.2,368.1
XS Rating Curve= 0 ,0
Exp/Cntr(USF)=0,0
Exp/Cntr=0.3,0.1

Type RM Length L Ch R = 1 ,648     ,103.6,94.4,84.2
XS GIS Cut Line= 4
2157745.96911693 463701.059569132157448.50706558463898.695330338
2157353.13810192 463962.79578132 2157282.7839484 464034.71336047
#Sta/Elev= 30
       0 3103.08    16.6 3100.55      31 3099.88    93.4 3097.46   146.2 3097.02
     175 3093.17   203.9 3094.85   217.1 3097.14     246 3097.77   260.4 3096.53
   284.1  3097.6   290.3 3096.99   304.7 3092.63   325.5 3093.72   344.7 3092.35
   357.5 3093.72   368.8  3093.8382.95193091.436   391.3 3090.59406.12193091.451
   415.4 3093.64   433.3 3092.29   440.5 3093.11   445.6 3094.83   473.4 3114.11
   482.9 3122.33   508.9 3146.94   520.1 3155.84   548.1 3170.24   572.6 3177.25
#Mann= 5 ,-1,0
       0     .12       0      30      .1       0382.9519    .045       0
406.1219      .1       0  512.04     .06       0
#XS Ineff= 2 , 0
          287.79 3100.61
Permanent Ineff=
       F       F
Bank Sta=382.9519,406.1219
XS Rating Curve= 0 ,0
Exp/Cntr(USF)=0,0
Exp/Cntr=0.3,0.1

Type RM Length L Ch R = 1 ,554     ,162,142,125.1
XS GIS Cut Line= 4
2157721.14352594463672.0622992882157564.84843275463685.429642784
 2157392.1012245463814.9900489752157255.34301796463992.878543189
#Sta/Elev= 30
       0 3098.79    49.1 3094.89    77.2 3091.39   137.5 3093.21   157.2  3092.7
   165.7 3090.65   197.7 3089.39   212.7 3093.73   227.7    3095   256.4 3093.27
   267.7 3094.42     280 3092.76     300 3092.39   312.7 3089.83   334.3 3092.34
   345.7 3091.94   356.4 3089.99   371.5 3091.32   379.2 3089.85   400.8 3088.74
   415.9 3089.82   425.7 3090.44   441.2 3088.44   459.9 3091.26   485.6 3089.21
   491.3 3090.57   526.9 3117.36   542.6 3130.22   569.6 3146.93   597.2 3170.05
#Mann= 5 ,-1,0
       0     .12       0     100      .1       0   379.2    .045       0
   415.9      .1       0  597.18     .06       0
#XS Ineff= 2 , 0
          370.75 3093.19
Permanent Ineff=
       F       F
Bank Sta=379.2,415.9
XS Rating Curve= 0 ,0
Exp/Cntr(USF)=0,0
Exp/Cntr=0.3,0.1

Type RM Length L Ch R = 1 ,412     ,127.6,149.5,195.2
XS GIS Cut Line= 4
2157675.90020949463552.7844650182157248.14521762463839.668221583
2157245.06044604463897.2506243342157192.61932925463962.030827429
#Sta/Elev= 30
       0 3092.07    28.6 3088.35      52 3086.81    71.9 3087.91   106.8 3091.36
     150 3090.81     173 3087.41   181.7 3087.43   202.3 3090.45   230.9 3093.24
   259.2 3092.08     288 3089.53   320.1 3089.02   346.4  3086.3   467.1 3090.91
   500.6 3087.42   524.1 3085.91   548.6 3084.74   556.6 3085.81   560.6 3090.41
   572.6  3107.2   587.5 3124.64   593.2 3130.81   599.6 3136.52   603.5 3141.73
   608.6 3147.25   618.6 3155.21   629.2 3161.01   644.7 3167.41   656.1 3171.09
#Mann= 4 ,-1,0
       0      .1       0   524.1    .045       0   556.6      .1       0
  592.72     .06       0
#XS Ineff= 2 , 0
          464.17 3100.48
Permanent Ineff=
       F       F
Bank Sta=524.1,556.6
XS Rating Curve= 0 ,0
Exp/Cntr(USF)=0,0
Exp/Cntr=0.3,0.1

Type RM Length L Ch R = 1 ,263     ,111.9,110.6,111
XS GIS Cut Line= 4
 2157672.0769312463535.9805833182157370.33578389463718.901382462
 2157134.2585132463740.7893413342157082.66546729463786.128684711
#Sta/Elev= 30
       0 3092.34    23.3 3090.38      56 3085.96   112.1  3090.6   135.5 3089.57
     161 3089.95   191.7 3085.39   196.3 3085.65   207.6 3088.94     225 3090.94
   247.8 3089.76   262.9 3090.67   289.9  3089.6   313.3 3088.34   322.6 3086.23
     332 3085.66     355 3086.62     379 3084.85   403.2 3085.09   427.3 3086.75
   491.6  3084.3   511.7 3085.56   531.8 3082.89  546.443079.181   559.1 3078.46
  571.783079.182   592.7 3096.12     603 3101.94   645.1  3116.5658.6304 3117.66
#Mann= 5 ,-1,0
       0      .1       0     290     .06       0     310      .1       0
  546.44    .045       0  571.78      .1       0
Bank Sta=546.44,571.78
XS Rating Curve= 0 ,0
Exp/Cntr(USF)=0,0
Exp/Cntr=0.5,0.3

Type RM Length L Ch R = 1 ,152     ,62,62.7,63.1
XS GIS Cut Line= 4
2157593.90564951463414.0333838892157346.88439939463604.771311201
2157067.03121095463639.1666751432156998.24048307463712.647679927
#Sta/Elev= 30
       0    3087     7.2 3085.81    44.4  3084.2    57.7 3082.25    74.8  3081.4
   116.4 3084.79   143.2 3085.48     169 3084.04   194.2 3085.53   208.8 3084.31
   214.4 3080.85   219.5 3078.91   228.8 3081.35   234.2 3083.68   244.8 3085.98
   308.6  3087.4   322.9 3085.58   330.9 3083.61   355.1 3081.99   447.7 3079.41
   458.4 3076.81  479.993074.971   496.2 3073.99  502.52 3074.97   532.4 3079.82
   548.6 3079.11   576.8 3079.58   629.7  3086.2   662.6 3092.81694.7054 3100.66
#Mann= 5 ,-1,0
       0     .06       0     140      .1       0     210     .06       0
  479.99    .045       0  502.52     .06       0
#XS Ineff= 2 , 0
          461.88 3083.29     520         3083.42
Permanent Ineff=
       F       F
Bank Sta=479.99,502.52
XS Rating Curve= 0 ,0
Exp/Cntr(USF)=0,0
Exp/Cntr=0.5,0.3

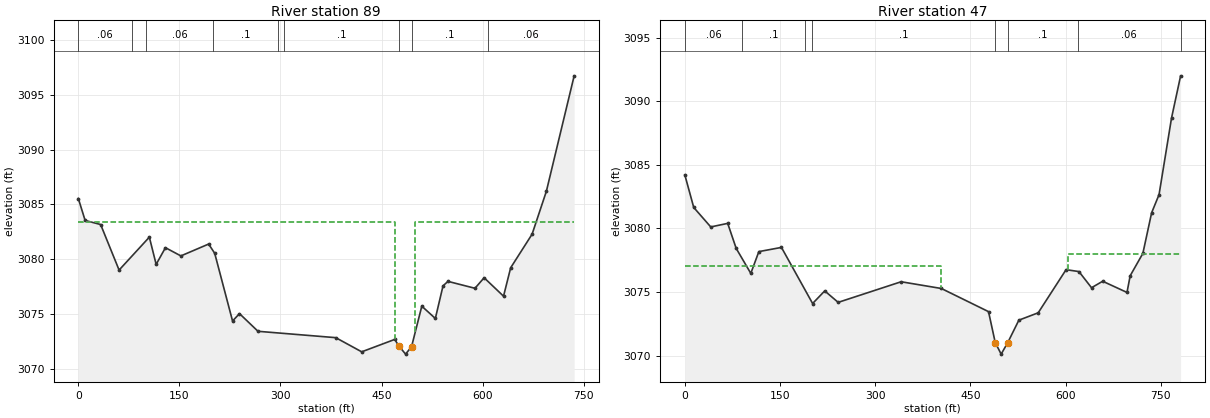
Type RM Length L Ch R = 1 ,89      ,43.5,41.9,39.1
XS GIS Cut Line= 5
2157597.03250078463354.6232098092157356.26495319463489.077814307
2157229.62747686 463557.868542192157071.72148785463573.502798527
2156968.53539603463692.323146689
#Sta/Elev= 30
       0 3085.54    10.1 3083.54    33.1 3083.17    60.5 3079.02   105.4 3082.02
   115.5 3079.54   129.3 3081.06   152.2 3080.31   193.4 3081.39   202.4 3080.55
   228.9 3074.38   239.2 3075.05   266.7 3073.44   382.1 3072.86   420.6 3071.57
   469.6  3072.7   475.8  3072.1   485.7 3071.36  494.583072.036   509.8 3075.73
   529.9 3074.61   541.3 3077.58   548.6 3077.99   588.7 3077.36   602.3 3078.32
   631.1 3076.64   641.7 3079.23   673.5 3082.29   694.7  3086.2735.9307 3096.72
#Mann= 9 ,-1,0
       0     .06       0      80      .1       0     100     .06       0
     200      .1       0  295.77     .06       0  305.77      .1       0
   475.8    .045       0  494.58      .1       0  608.56     .06       0
#XS Ineff= 2 , 0
             470 3083.42     500         3083.42
Permanent Ineff=
       F       F
Bank Sta=475.8,494.58
XS Rating Curve= 0 ,0
Exp/Cntr(USF)=0,0
Exp/Cntr=0.5,0.3

Type RM Length L Ch R = 1 ,47      ,,,
XS GIS Cut Line= 4
2157604.84962895463318.6644202332157210.86636925463512.529198813
2157031.07242138463550.0514140222156935.70345772463676.688890352
#Sta/Elev= 30
       0 3084.22    14.1 3081.65    40.9 3080.12    67.6  3080.4      81 3078.43
     104 3076.47   116.7 3078.18   152.3 3078.51   201.4  3074.1   220.5 3075.09
   241.7 3074.19   340.9 3075.81   404.3 3075.28   478.6 3073.46  489.153071.034
   498.5 3070.12  508.983071.034   526.4 3072.79   556.9 3073.37   600.8 3076.76
   621.1 3076.61   640.9 3075.34   658.5 3075.85   696.8 3074.97   701.8 3076.28
   721.8 3078.04   735.6 3081.23   747.3 3082.66     767 3088.69781.2964    3092
#Mann= 8 ,-1,0
       0     .06       0      90      .1       0     190     .06       0
     200      .1       0  489.15    .045       0  508.98      .1       0
   619.1     .06       0   781.3      .1       0
#XS Ineff= 2 , 0
          403.96 3077.08  603.74         3077.99
Permanent Ineff=
       F       F
Bank Sta=489.15,508.98
XS Rating Curve= 0 ,0
Exp/Cntr(USF)=0,0
Exp/Cntr=0.3,0.1
LCMann Table=0

Chan Stop Cuts=-1
Use User Specified Reach Order=0
Composite Channel Slope=5